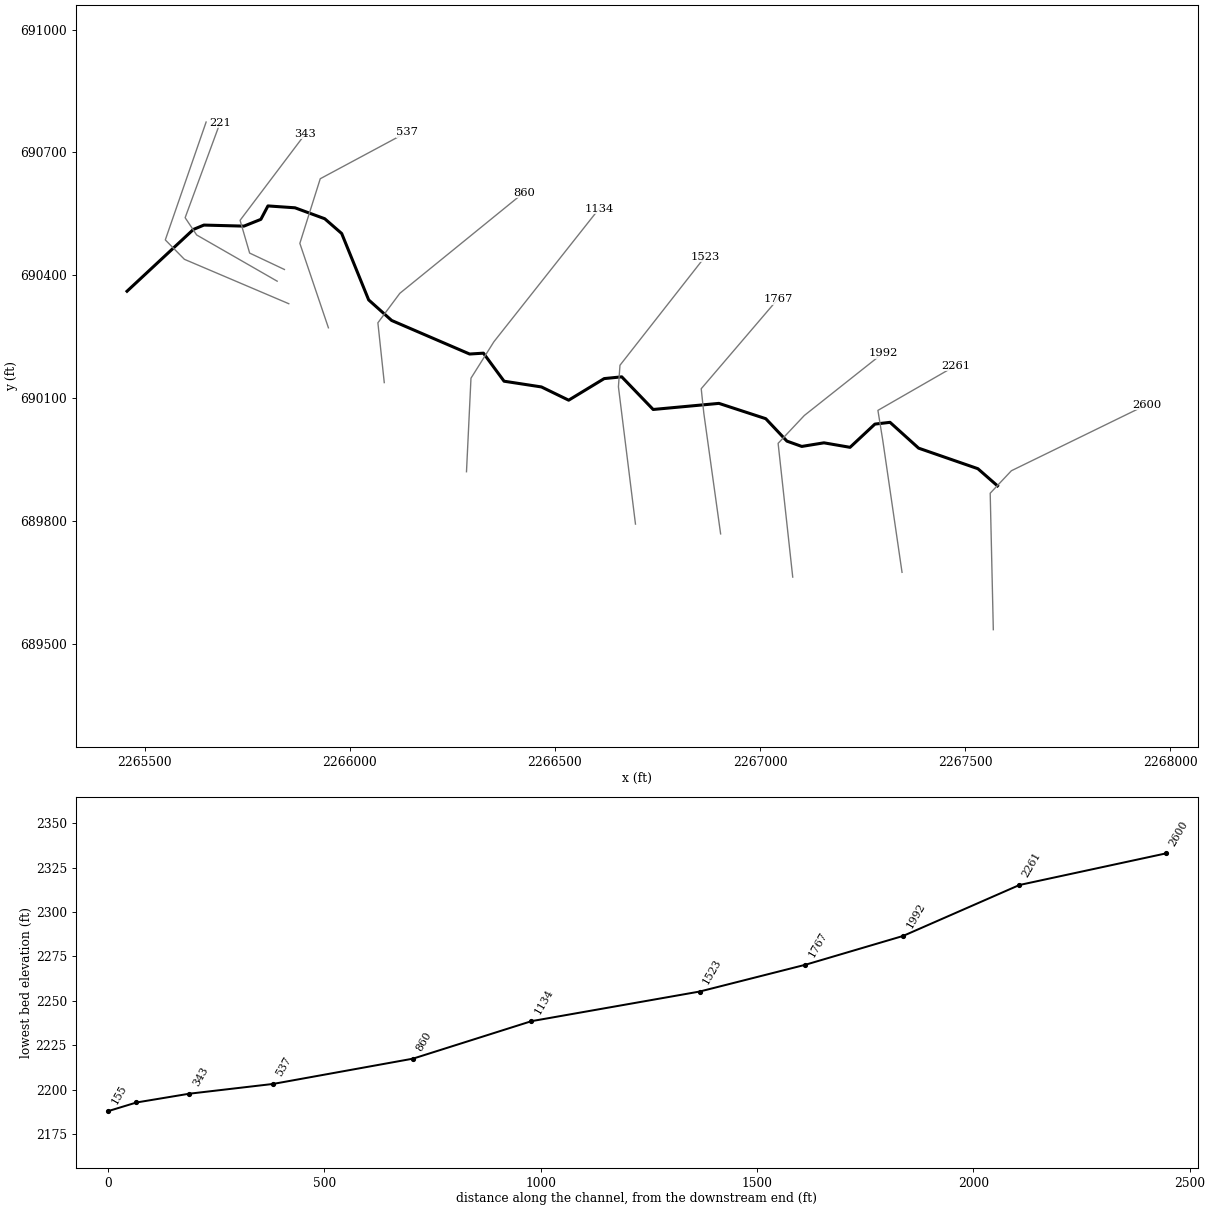
--- ROARCKT4.prj (project) ---

Proj Title=ROARCKT4
Current Plan=p01
Default Exp/Contr=0,0
English Units
Geom File=g01
Flow File=f01
Plan File=p01
BEGIN DESCRIPTION:
----------MODEL BY WOOD PLC 2022----------
AFH study
Randolph County, WV
HEC-RAS Version: RAS 6.2
Vertical Datum: NAVD88
Projection: NAD 1983 StatePlane West Virginia S FIPS 4702 (US Feet)
Terrain: 1-meter LIDAR (FEMA Region III 3DEP collected 2016-2018)
Land Use: 2019 NLCD
Hydrologic Method:
WV SIR2010-5033 regression equations
Additional Model Notes:
None
END DESCRIPTION:
DSS Export Rating Curves= 0
DSS Export Rating Curve Sorted= 0
DSS Export Volume Flow Curves= 0
DXF OffsetX= 0
DXF OffsetY= 0
DXF ScaleX= 0
DXF ScaleY= 0

--- ROARCKT4.p01 (plan) ---

Plan Title=Floodplain
Program Version=6.20
Short Identifier=Floodplain
Geom File=g01
Flow File=f01
Subcritical Flow
K Sum by GR= 0
Std Step Tol= 0.01
Critical Tol= 0.01
Num of Std Step Trials= 20
Max Error Tol= 0.3
Flow Tol Ratio= 0.001
Split Flow NTrial= 30
Split Flow Tol= 0.02
Split Flow Ratio= 0.02
Log Output Level= 0
Friction Slope Method= 1
Unsteady Friction Slope Method= 2
Unsteady Bridges Friction Slope Method= 1
Parabolic Critical Depth
Global Vel Dist= 0 , 0 , 0
Global Log Level= 0
CheckData=True
Encroach Param=-1 ,0,0, 0
Mapping Interval=1HOUR
Computation Time Step Use Courant=        0
Computation Time Step Use Time Series=    0
Computation Time Step Count To Double=0
Computation Time Step Max Doubling=0
Computation Time Step Max Halving=0
Computation Time Step Residence Courant=0
Run HTab= 0
Run UNet= 0
Run Sediment= 0
Run PostProcess= 0
Run WQNet= 0
Run RASMapper=-1
UNET Theta= 0
UNET Theta Warmup= 0
UNET ZTol= 0
UNET ZSATol= 0
UNET MxIter= 0
UNET Max Iter WO Improvement= 0
UNET MaxInSteps= 0
UNET DtIC= 0
UNET DtMin= 0
UNET MaxCRTS= 0
UNET WFStab= 0
UNET SFStab= 0
UNET WFX= 1
UNET SFX= 1
UNET Gravity=32.174
UNET 1D Methodology=Finite Difference
UNET DSS MLevel= 1
UNET Pardiso=0
UNET DZMax Abort= 0
UNET Use Existing IB Tables= 0
UNET Froude Reduction=False
UNET Froude Limit= 0
UNET Froude Power= 0
UNET D1 Cores= 0
UNET WindReference=Eulerian
UNET WindDragFormulation=Hsu (1988)
UNET D2 Coriolis=0
UNET D2 Cores= 0
UNET D2 Theta= 1
UNET D2 Theta Warmup= 1
UNET D2 Z Tol= 0.01
UNET D2 Volume Tol= 0.01
UNET D2 Max Iterations= 20
UNET D2 Equation= 0
UNET D2 RampUpFraction=0.1
UNET D2 TimeSlices= 1
UNET D2 Turbulence Formulation=Non-Conservative (original)
UNET D2 Eddy Viscosity=0.3
UNET D2 Transverse Eddy Viscosity=0.1
UNET D2 Smagorinsky Mixing=0
UNET D2 BCVolumeCheck=0
UNET D2 Cores=0
UNET D2 SolverType=PARDISO (Direct)
UNET D2 Minimum Iterations= 2147483647
UNET D2 Maximum Iterations= 2147483647
UNET D2 Restart Number= 10
UNET D2 Relaxation Coeff=1.3
UNET D2 SOR Precondition Iterations= 10
UNET D2 ILUT Maximum Fill= 8
UNET D2 ILUT Tolerance=1E-08
UNET D1D2 MaxIter= 0
UNET D1D2 ZTol=0.01
UNET D1D2 QTol=0.1
UNET D1D2 MinQTol=1
Write IC File= 0
Write IC File at Fixed DateTime=0
Write IC File at Sim End=0
Echo Input=False
Echo Parameters=False
Echo Output=False
Write Detailed= 0
HDF Write Warmup=0
HDF Write Time Slices=0
HDF Flush=0
HDF Compression= 1
HDF Chunk Size= 1
HDF Spatial Parts= 1
HDF Use Max Rows=0
HDF Fixed Rows= 1
Calibration Method= 0
Calibration Iterations= 20
Calibration Max Change=0.05
Calibration Tolerance=0.2
Calibration Maximum=1.5
Calibration Minimum=0.5
Calibration Optimization Method= 1
WQ AD Non Conservative
WQ ULTIMATE=-1
WQ Max Comp Step=1HOUR
WQ Output Interval=15MIN
WQ Output Selected Increments= 0
WQ Output face flow=0
WQ Output face velocity=0
WQ Output face area=0
WQ Output face dispersion=0
WQ Output cell volume=0
WQ Output cell surface area=0
WQ Output cell continuity=0
WQ Output cumulative cell continuity=0
WQ Output face conc=0
WQ Output face dconc_dx=0
WQ Output face courant=0
WQ Output face peclet=0
WQ Output face adv mass=0
WQ Output face disp mass=0
WQ Output cell mass=0
WQ Output cell source sink temp=0
WQ Output nsm pathways=0
WQ Output nsm derived pathways=0
WQ Create Restart=0
WQ Fixed Restart=0
WQ System Summary=0
WQ Write To DSS=0
Sorting and Armoring Iterations= 10
XS Update Threshold= 0.02
Bed Roughness Predictor= 0
Hydraulics Update Threshold= 0.02
Energy Slope Method= 1
Volume Change Method= 1
Sediment Retention Method= 0
Sediment TS Multiplier= 1
Warm Up Method= 0
XS Weighting Method= 0
Number of US Weighted Cross Sections= 1
Number of DS Weighted Cross Sections= 1
Upstream XS Weight=0
Main XS Weight=1
Downstream XS Weight=0
Number of DS XS's Weighted with US Boundary= 1
Upstream Boundary Weight= 1
Weight of XSs Associated with US Boundary= 0
Number of US XS's Weighted with DS Boundary= 1
Downstream Boundary Weight= 0.5
Weight of XSs Associated with DS Boundary= 0.5
Percentile Method= 0
Sediment Output Level= 3
Mass or Volume Output= 0
Output Increment Type= 1
Profile and TS Output Increment= 1
Transport Output Increment 1
XS Output Flag= 0
XS Output Increment= 10
Read HDF5 Sediment Hotstart= 0
Sediment Hotstart Type= 0
Write Gradation File= 0
Read Gradation Hotstart= 0
Write HDF5 File= 1
Write Binary Output= 1
Write DSS Sediment File= 0
DSS Sediment Output Type= 1
SV Curve= 0
Specific Gage Flag= 0
Subcell Erosion Methods= 0
Subcell Deposition Methods= 0
Advection Scheme= 1
Matrix Solver= 0
Implicit Weighting Factor= 1
Maximum Outer Loop Convergence Iterations= 5
Convergence Maximum Absolute= 0.001
Convergence RMSE= 0.0001
Grain Fractions Max Abs Error= 0.001
Max Subgrid Regions= 1
Max Subgrid Length Scale= 3.402823E+38
Initial Layer Thickness= 3.402823E+38
Min Layer Thickness= 3.402823E+38
Max Layer Thickness= 3.402823E+38
Number of Layers= 5

--- ROARCKT4.f01 (steady flow) ---

Flow Title=Flow
Program Version=6.20
Number of Profiles= 1
Profile Names=P100yr
River Rch & RM=ROARCKT4,Main,2600
     361
Boundary for River Rch & Prof#=ROARCKT4,Main            , 1
Up Type= 0
Dn Type= 3
Dn Slope=0.07416
DSS Import GetInterval= 0
DSS Import GetPeak= 0
DSS Import FillOption= 0

--- ROARCKT4.g01 (geometry) ---

Geom Title=Geometry
Program Version=6.20

River Reach=ROARCKT4        ,Main
Reach XY= 30
2267579.08102334689886.3583359422267531.26403265689928.268290818
2267386.76800001689978.391000003     2267317.057690041.412000015
2267280.21899998690037.1240000132267219.59900001689980.429000005
2267155.94599998689991.4120000152267101.90500003689982.601999998
2267065.66899998689995.5789999962267014.11499998690050.312999994
2266899.92300001690087.6820000112266739.55400001690072.803000018
     2266662.969      690152.4562266620.20000003690148.192000017
2266533.54200003690095.469000012     2266467.146690127.803000018
2266376.04199998690141.7980000082266325.76181993 690210.24174712
2266292.05518483690208.1350824272266101.91500004690290.053000003
2266045.90900002690340.2240000072265980.13400003690502.295000017
2265938.79300003690538.3349999932265866.36300004690565.023000002
2265800.35155752 690569.60640423     2265783.058690536.800999999
2265741.83014508690520.310855009       2265644.2690522.855000019
2265618.59725775690512.206453711 2265456.7562717690361.402204067

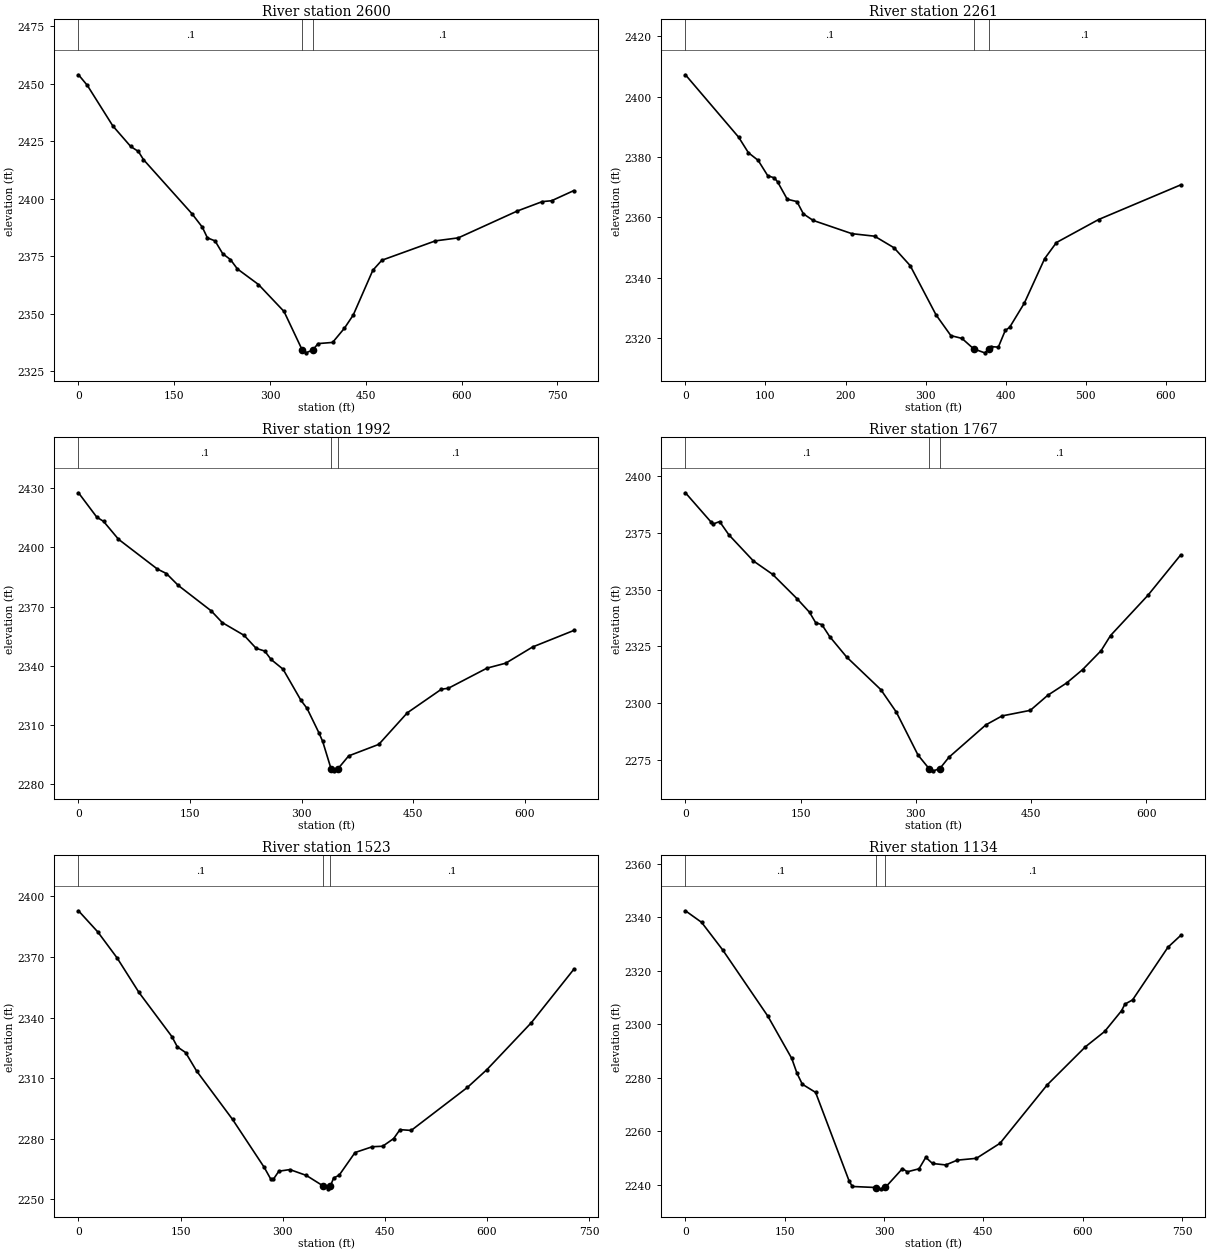
Type RM Length L Ch R = 1 ,2600    ,329.5,338.6,346.2
XS GIS Cut Line= 4
 2267568.9051574689535.363370031 2267561.3008377689868.399783454
2267612.88196841689923.2319660352267942.80607622 690084.36622094
#Sta/Elev= 30
       0 2453.97    13.8 2449.38    53.8 2431.72    81.8 2422.78    93.8 2420.62
   101.8 2417.07   177.9 2393.48   193.9 2387.71   201.9 2383.05   213.9 2381.72
   225.9 2376.14   237.9 2373.62   248.9 2369.53   281.9 2362.76   321.9 2351.03
  350.432334.265   356.2 2333.04  366.732334.261   375.3 2337.06     398 2337.57
   416.5 2343.75   430.3 2349.48     461 2368.95   475.1 2373.31   558.9 2381.73
   594.8 2383.04   687.5 2394.75   726.4 2398.81     741 2399.19   775.6 2403.58
#Mann= 3 ,-1,0
       0      .1       0  350.43    .045       0  366.73      .1       0
Bank Sta=350.43,366.73
XS Rating Curve= 0 ,0
Exp/Cntr=0.3,0.1

Type RM Length L Ch R = 1 ,2261    ,273.9,268.7,265.4
XS GIS Cut Line= 4
2267346.34197784689675.3297368082267299.37679502689997.509071079
 2267287.5424987690070.5903299512267477.43992481690179.899708528
#Sta/Elev= 30
       0 2407.19    66.5 2386.54    78.7  2381.4    90.8  2378.9   102.9 2373.78
     111 2373.11   115.1  2371.8   127.2 2366.03   139.3 2365.25   147.4 2361.18
   159.5 2359.03     208 2354.64   236.3 2353.81   260.6 2349.98   280.8 2344.07
   313.1 2327.78   331.6 2320.93   345.5    2320  360.142316.539   373.9 2315.23
   379.3 2316.55     382 2317.29   390.9 2317.11   399.6 2322.65     405 2323.65
   423.4 2331.67   448.8 2346.39   463.5 2351.71   516.2 2359.32   618.7 2370.77
#Mann= 3 ,-1,0
       0      .1       0  360.14    .045       0   379.3      .1       0
Bank Sta=360.14,379.3
XS Rating Curve= 0 ,0
Exp/Cntr(USF)=0,0
Exp/Cntr=0.3,0.1

Type RM Length L Ch R = 1 ,1992    ,219.3,225.4,229.9
XS GIS Cut Line= 4
 2267079.8319065689663.704655789 2267044.2145073689990.149146612
2267108.10712747690058.1200191312267299.53589407690209.988280133
#Sta/Elev= 30
       0 2427.77    24.6  2415.4    33.7 2413.25    53.8 2404.16   106.1 2389.03
   118.2 2386.76   134.3 2380.68   178.5 2367.79   193.3 2361.85   222.8 2355.34
   238.9 2348.77   250.5 2347.37     259 2343.11   275.1 2338.17   299.2 2322.34
   307.3 2318.31   323.4 2305.81   328.4 2301.48  339.552287.716   343.5 2286.54
  349.212287.718   363.4 2294.14   403.9 2299.99   442.2 2316.01   488.1    2328
   497.4 2328.48   549.4 2338.71   574.6 2341.22   610.7 2349.45     666 2357.82
#Mann= 3 ,-1,0
       0      .1       0  339.55    .045       0  349.21      .1       0
Bank Sta=339.55,349.21
XS Rating Curve= 0 ,0
Exp/Cntr(USF)=0,0
Exp/Cntr=0.3,0.1

Type RM Length L Ch R = 1 ,1767    ,246.2,244.4,242.3
XS GIS Cut Line= 4
2266904.04051485689769.143611933 2266863.1127746690063.311744983
2266856.71781519690123.4243634752267043.45063008690342.131975438
#Sta/Elev= 30
       0  2392.5      33 2379.78    36.4 2378.82    44.5 2379.86    56.6 2374.02
    88.5 2362.55   113.4  2356.7   145.4 2345.95   161.6    2340   169.7 2335.37
   177.7 2334.58   187.8 2329.35     210 2320.32   254.5 2306.01   274.7 2296.12
   302.9 2277.28  317.212271.345     323 2270.33  331.422271.346   343.1 2276.27
   391.3 2290.53   412.4 2294.46   449.2 2296.91   471.8  2303.5   496.5 2308.93
   517.2 2314.78   541.4 2323.14   553.7 2329.79   602.3 2347.43     645 2365.18
#Mann= 3 ,-1,0
       0      .1       0  317.21    .045       0  331.42      .1       0
Bank Sta=317.21,331.42
XS Rating Curve= 0 ,0
Exp/Cntr(USF)=0,0
Exp/Cntr=0.3,0.1

Type RM Length L Ch R = 1 ,1523    ,391.3,388.7,384.6
XS GIS Cut Line= 4
2266696.43823229689793.0547953622266654.86028154690128.159646472
2266658.66467925 690180.749526192266866.40494961690446.079734725
#Sta/Elev= 30
       0 2392.91    28.3 2382.46    56.6 2369.62    88.8 2352.48   137.2 2330.62
   145.2 2325.52   157.3 2322.73   173.4 2313.63   226.3  2289.6   272.9 2265.81
   282.3 2260.11   286.3 2260.01   294.3 2263.96   310.5 2264.77   334.7 2261.87
  359.762256.574   366.8 2255.23  369.952256.574   374.8 2260.64   382.8 2261.94
   406.2 2273.21   431.6 2276.08   446.8 2276.32     463 2280.14   472.2 2284.54
   488.7 2284.15   571.3 2305.46   599.8 2314.23   665.3 2337.55   727.4 2363.88
#Mann= 3 ,-1,0
       0      .1       0  359.76    .045       0  369.95      .1       0
Bank Sta=359.76,369.95
XS Rating Curve= 0 ,0
Exp/Cntr=0.3,0.1

Type RM Length L Ch R = 1 ,1134    ,272.5,273.8,272.3
XS GIS Cut Line= 4
2266284.42299506689920.8502331882266295.36221297690149.131875198
2266351.26557875690238.139741154 2266608.0782962690563.244906806
#Sta/Elev= 30
       0  2342.5    24.4 2338.18    56.4 2327.82   124.5 2303.09   160.6 2287.28
   168.5 2281.75   176.5 2277.66   196.6  2274.6   247.5 2241.31   252.2 2239.42
   287.2 2239.04   294.7 2238.54  301.872239.047   327.8  2246.1   335.1 2244.91
   352.8 2246.03     363  2250.3   373.2 2248.02   393.2 2247.47   410.5 2249.26
   439.5 2249.95   475.2 2255.58   546.5 2277.43   604.2 2291.66   633.2 2297.37
   658.7 2305.12   663.8  2307.6   675.4 2309.18   728.8 2328.87     748 2333.27
#Mann= 3 ,-1,0
       0      .1       0   287.2    .045       0  301.87      .1       0
Bank Sta=287.2,301.87
XS Rating Curve= 0 ,0
Exp/Cntr(USF)=0,0
Exp/Cntr=0.3,0.1

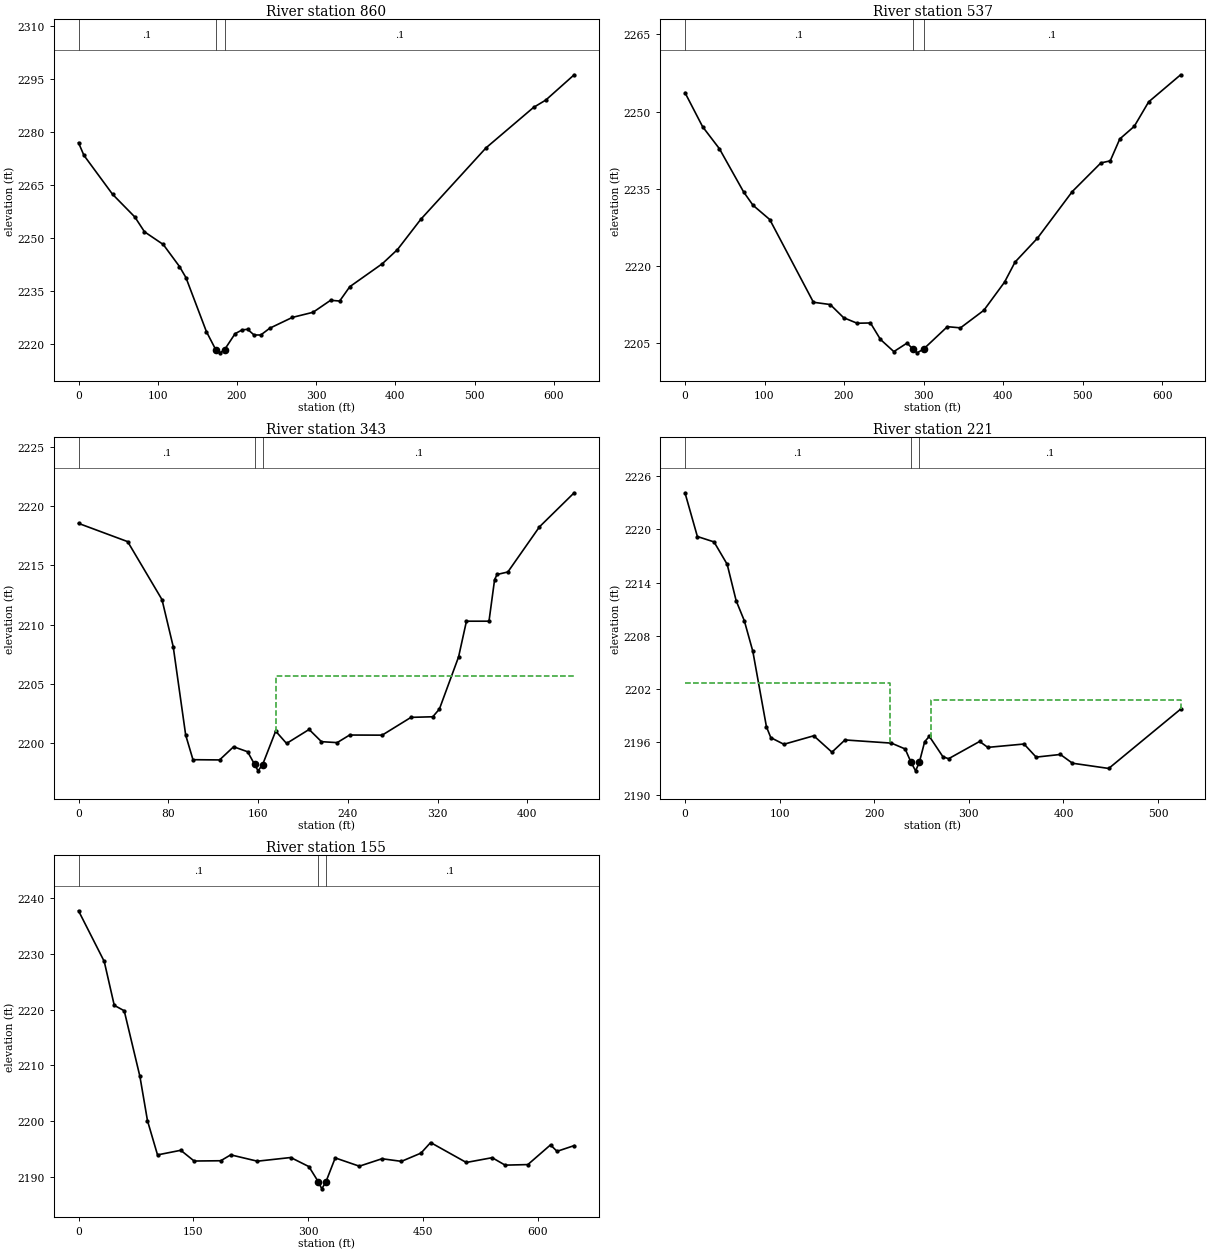
Type RM Length L Ch R = 1 ,860     ,316.9,323.4,322.5
XS GIS Cut Line= 4
2266083.94335102690138.3728557842266068.40515942690284.338746606
2266121.87043601690356.2864589352266423.94949693690601.980210916
#Sta/Elev= 30
       0 2277.02     6.8 2273.45      43 2262.39    71.2 2255.93    83.3 2251.75
     107 2248.15   127.5  2241.9   135.6 2238.78   161.5 2223.43   173.2 2218.35
   178.7 2217.42   184.4 2218.33   197.7 2222.86   206.8 2223.94   213.5 2224.09
   221.6 2222.49   230.1 2222.48   241.5 2224.41     270 2227.47   296.1 2228.92
   318.3 2232.33   329.7 2232.11   342.5 2236.18   383.7 2242.72   402.7 2246.71
   432.1 2255.28   514.5 2275.56   574.5 2287.03     590 2289.12   625.8 2296.29
#Mann= 3 ,0,0
       0      .1       0   173.2    .045       0   184.4      .1       0
Bank Sta=173.2,184.4
XS Rating Curve= 0 ,0
Exp/Cntr=0.3,0.1

Type RM Length L Ch R = 1 ,537     ,185.3,193.5,194.6
XS GIS Cut Line= 4
2265947.76441852690272.1544361732265878.13041601690478.214239517
2265927.86898924690635.9565717312266139.61320095690749.644739093
#Sta/Elev= 30
       0 2253.69    22.2 2247.07    43.3  2242.8    73.7 2234.42    85.5 2231.83
   106.6 2229.05   161.5 2212.99   182.6 2212.55   199.5 2209.99   216.4 2208.92
   233.2 2208.97   245.8 2205.77   262.6 2203.41   279.3 2205.07  286.42  2203.9
   291.9 2203.17  299.942203.898   329.9 2208.25   346.4 2208.02   375.8 2211.43
   401.8  2216.9     415 2220.79   443.1 2225.42     487 2234.49   522.9 2240.04
   534.7 2240.45   546.7  2244.7   564.9 2247.15     583  2251.9   623.2 2257.16
#Mann= 3 ,-1,0
       0      .1       0  286.42    .045       0  299.94      .1       0
Bank Sta=286.42,299.94
XS Rating Curve= 0 ,0
Exp/Cntr(USF)=0,0
Exp/Cntr=0.3,0.1

Type RM Length L Ch R = 1 ,343     ,121.2,121.9,124.3
XS GIS Cut Line= 4
2265840.49326242690414.4834809162265755.71924254690454.526617276
2265732.40688071690534.4832794572265891.72500634690745.815686184
#Sta/Elev= 30
       0 2218.54    43.8    2217    74.4 2212.11    84.4 2208.14    95.5 2200.69
     102 2198.61   125.7 2198.59   138.2  2199.7   150.7 2199.28156.84982198.225
     160 2197.67164.06982198.197   175.7 2201.02   185.4 2199.98   205.5 2201.16
   216.5 2200.13   230.5 2200.05   241.6 2200.69   270.6 2200.68   296.3 2202.18
   315.7 2202.23   321.6 2202.88   338.7 2207.28   345.7 2210.29   365.8 2210.29
   370.8  2213.8     373 2214.23   382.6 2214.44   410.8 2218.25   441.7 2221.12
#Mann= 3 ,-1,0
       0      .1       0156.8498    .045       0164.0698      .1       0
#XS Ineff= 2 , 0
                          176.37         2205.71
Permanent Ineff=
       F       F
Bank Sta=156.8498,164.0698
XS Rating Curve= 0 ,0
Exp/Cntr(USF)=0,0
Exp/Cntr=0.3,0.1

Type RM Length L Ch R = 1 ,221     ,65.5,66.3,67.2
XS GIS Cut Line= 4
2265822.80183577 690385.942081232265626.53620645690498.724579877
2265598.44092209690540.8675064182265683.60235556690772.448761974
#Sta/Elev= 30
       0 2224.14    13.1  2219.2    30.7 2218.59    44.6 2216.06    54.1 2211.94
    62.7 2209.69    71.7 2206.23    86.1  2197.7    90.7 2196.48   104.5 2195.73
   136.1 2196.69   155.3 2194.84   169.1 2196.22   218.2 2195.86   232.7  2195.2
   238.9 2193.69   243.7 2192.73  247.652193.685   253.3 2196.02   258.2 2196.63
   272.6 2194.32   278.6  2194.1   311.4 2196.05     320 2195.38   358.3 2195.76
   371.1 2194.28   396.7 2194.58   409.5 2193.59   447.8    2193   523.8  2199.7
#Mann= 3 ,-1,0
       0      .1       0   238.9    .045       0  247.65      .1       0
#XS Ineff= 2 , 0
          216.36  2202.6  259.48         2200.75
Permanent Ineff=
       F       F
Bank Sta=238.9,247.65
XS Rating Curve= 0 ,0
Exp/Cntr(USF)=0,0
Exp/Cntr=0.3,0.1

Type RM Length L Ch R = 1 ,155     ,,,
XS GIS Cut Line= 4
2265851.10732233690330.9362646112265596.64431827690439.303789999
2265550.08641847690486.6644122052265649.60748043690774.355058859
#Sta/Elev= 30
       0 2237.78    33.6 2228.67    46.7 2220.78    59.7 2219.81    80.2    2208
    90.1 2200.04   103.2  2193.9   133.6 2194.73     151  2192.8   185.8 2192.85
   198.8 2193.91   233.6 2192.77   277.2 2193.43   300.9  2191.8  313.192189.073
   317.8  2187.8  323.192189.073   335.3 2193.36   366.8 2191.87   396.4 2193.21
   421.8 2192.74   447.3 2194.22   459.9 2196.12   506.5 2192.54   540.3  2193.4
   557.2 2192.06   586.9 2192.16   616.5  2195.7     625 2194.54   647.4 2195.57
#Mann= 3 ,-1,0
       0      .1       0  313.19    .045       0  323.19      .1       0
Bank Sta=313.19,323.19
XS Rating Curve= 0 ,0
Exp/Cntr(USF)=0,0
Exp/Cntr=0.3,0.1
LCMann Table=0

Chan Stop Cuts=-1
Use User Specified Reach Order=0
Composite Channel Slope=5